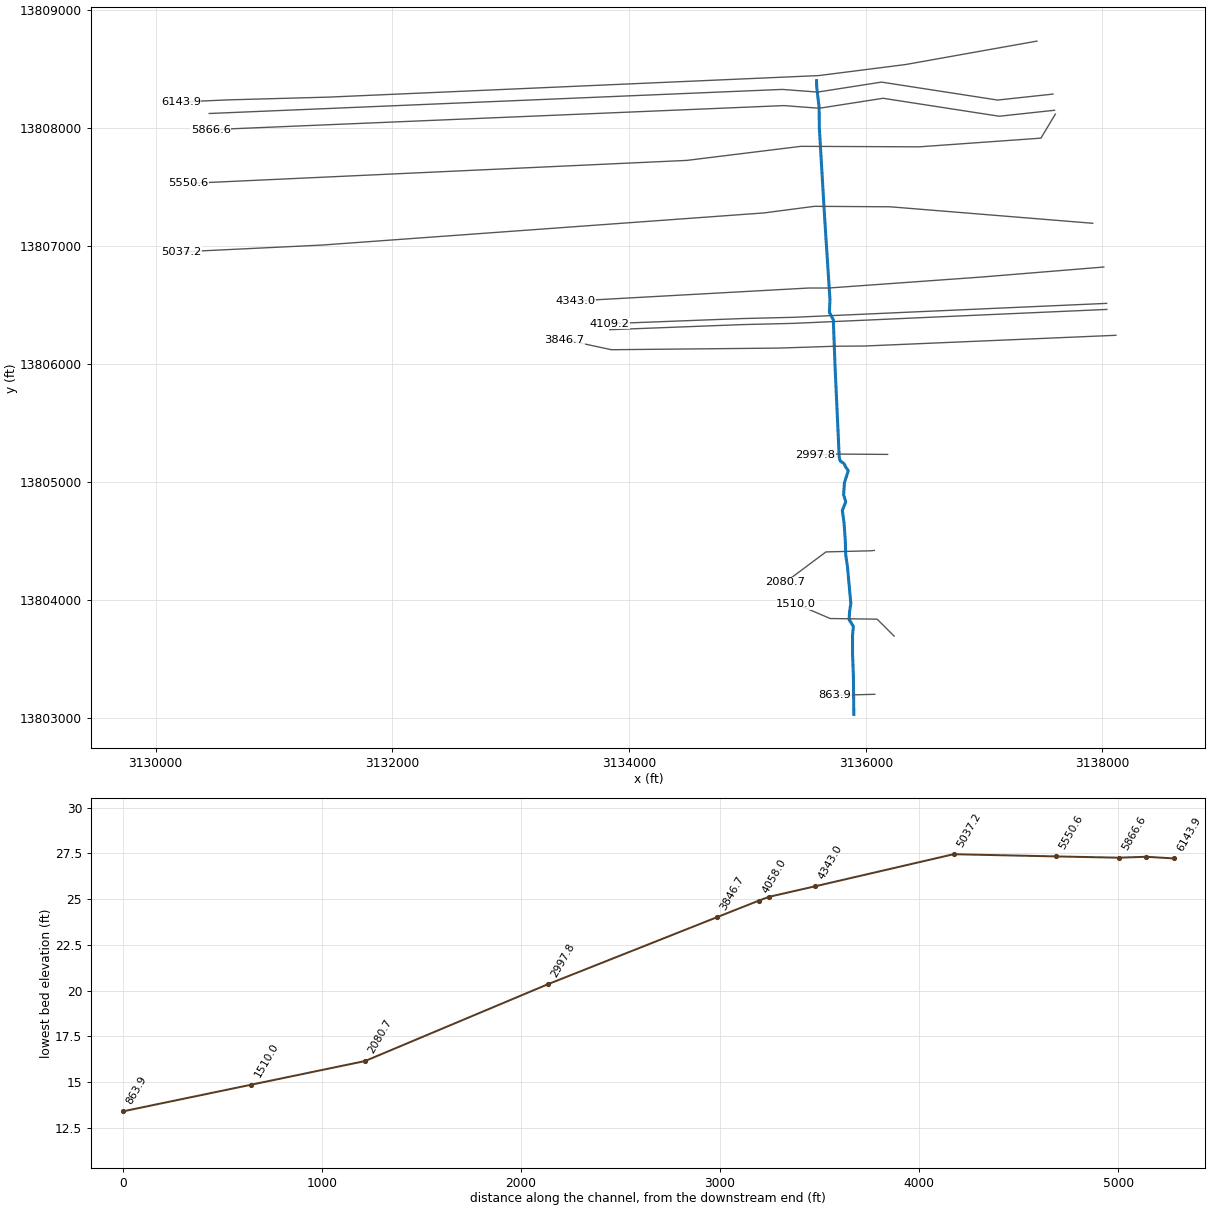
--- C118-00-00.PRJ (project) ---

Proj Title=C118-00-00
Current Plan=p02
Default Exp/Contr=0.3,0.1
English Units
Geom File=g01
Flow File=f01
Flow File=f02
Plan File=p01
Plan File=p02
Y Axis Title=Elevation
X Axis Title(PF)=Main Channel Distance
X Axis Title(XS)=Station
BEGIN DESCRIPTION:
Sims Bayou Watershed
Tributary 10.12 to Sims Bayou
HCFCD Unit C118-00-00
Flood Hazard Model
10, 2, 1, 0.2% Event
Filename C118-00-00.prj
Prepared by:  Watershed Concepts  Date:
Reviewed by:                      Date:
STATUS FINAL
END DESCRIPTION:
DSS Export Rating Curves= 0
DSS Export Rating Curve Sorted= 0
DSS Export Volume Flow Curves= 0
DXF OffsetX= 0
DXF OffsetY= 0
DXF ScaleX= 1
DXF ScaleY= 10

--- C118-00-00.p02 (plan) ---

Plan Title=Effective Floodway 2015
Program Version=4.10
Short Identifier=Eff+RiskMAP FW
Geom File=g01
Flow File=f02
Subcritical Flow
K Sum by GR= 0
Std Step Tol= 0.01
Critical Tol= 0.01
Num of Std Step Trials= 20
Max Error Tol= 0.3
Flow Tol Ratio= 0.001
Split Flow NTrial= 30
Split Flow Tol= 0.02
Split Flow Ratio= 0.02
Log Output Level= 0
Friction Slope Method= 1
Unsteady Friction Slope Method= 2
Unsteady Bridges Friction Slope Method= 1
Parabolic Critical Depth
Global Vel Dist= 0 , 0 , 0
Global Log Level= 0
CheckData=True
Encroach Param=-1 ,0,0, 2
Encroach River=C118-00-00
Encroach Reach=Reach - 1
Encroach Node=6143.9
       1  4971.4  5024.7
Encroach Node=6004.2
       1    4955    5045
Encroach Node=5935.4
       1    4955    5045
Encroach Node=5866.6
       1    4955    5045
Encroach Node=5550.6
       1    4969    5022
Encroach Node=5037.2
       1    4969    5022
Encroach Node=4343.0
       1  4975.5  5035.5
Encroach Node=4109.2
       1  4965.6  5036.4
Encroach Node=4083.6
       1  4975.6  5035.4
Encroach Node=4058.0
       1  4975.6  5035.4
Encroach Node=3846.7
       1  4949.1  5046.1
Encroach Node=2997.8
       1  4955.8  5043.8
Encroach Node=2080.7
       1  4970.6  5026.4
Encroach Node=1510.0
       1  4945.4  5065.4
Encroach Node=863.9
       1  4965.9  5042.4
Encroach Reach=C118-00-00_0009
Encroach Node=6143.9
       1  4971.4  5024.7
Encroach Node=6004.2
       1    4955    5045
Encroach Node=5935.4
       1    4955    5045
Encroach Node=5866.6
       1    4955    5045
Encroach Node=5550.6
       1    4969    5022
Encroach Node=5037.2
       1    4969    5022
Encroach Node=4343.0
       1  4975.5  5035.5
Encroach Node=4109.2
       1  4965.6  5036.4
Encroach Node=4083.6
       1  4975.6  5035.4
Encroach Node=4058.0
       1  4975.6  5035.4
Encroach Node=3846.7
       1  4949.1  5046.1
Encroach Node=2997.8
       1  4955.8  5043.8
Encroach Node=2080.7
       1  4970.6  5026.4
Encroach Node=1510.0
       1  4945.4  5065.4
Encroach Node=863.9
       1  4965.9  5042.4
BEGIN DESCRIPTION:
FEMA Effective Risk Map Study Floodway May 02, 2019
END DESCRIPTION:
Computation Interval=1HOUR
Output Interval=1HOUR
Run HTab= 0
Run UNet= 0
Run PostProcess= 0
Run WQNet= 0
UNET Theta= 1
UNET Theta Warmup= 1
UNET ZTol= 0.02
UNET ZSATol= 0.1
UNET MxIter= 20
UNET MaxInSteps= 20
UNET DtIC= 0
UNET DtMin= 0
UNET MaxCRTS= 20
UNET WFStab= 2
UNET SFStab= 1
UNET WFX= 1
UNET SFX= 1
UNET DSS MLevel= 4
UNET DZMax Abort= 100
UNET Convert EG Bridges=-1
UNET Use Existing IB Tables=-1
UNET Froude Reduction=False
UNET Froude Limit= 1
UNET Froude Power= 10
UNET Time Slicing=0,0, 5
UNET Junction Losses=0
Instantaneous Interval=1HOUR
Write IC File= 0
IC Time=0,,
Write IC File at Sim End=0
Echo Input=False
Echo Parameters=False
Echo Output=False
Write Detailed= 0
WQ AD Non Conservative
WQ ULTIMATE=-1
WQ Max Comp Step=1HOUR
WQ Output Interval=15MIN
WQ Output Selected Increments= 0
WQ Output face flow=0
WQ Output face velocity=0
WQ Output face area=0
WQ Output face dispersion=0
WQ Output cell volume=0
WQ Output cell surface area=0
WQ Output cell continuity=0
WQ Output cumulative cell continuity=0
WQ Output face conc=0
WQ Output face dconc_dx=0
WQ Output face courant=0
WQ Output face peclet=0
WQ Output face adv mass=0
WQ Output face disp mass=0
WQ Output cell mass=0
WQ Output cell source sink temp=0
WQ Output cell source sink nsm=0
WQ Output MaxMinRange=-1
WQ Daily Max Min Mean=-1
WQ Daily Range=0
WQ Daily Time=0
WQ Create Restart=0
WQ Fixed Restart=0
WQ System Summary=0
WQ Use Fixed Temperature=0
Sorting and Armoring Iterations= 10
XS Update Threshold= 0.02
Hydraulics Update Threshold= 0.02
Energy Slope Method= 1
Volume Change Method= 0
XS Weighting Method= 0
Number of US Weighted Cross Sections= 1
Number of DS Weighted Cross Sections= 1
Upstream XS Weight=0.25
Main XS Weight=0.5
Downstream XS Weight=0.25
Number of DS XS's Weighted with US Boundary= 1
Upstream Boundary Weight= 1
Weight of XSs Associated with US Boundary= 0
Number of US XS's Weighted with DS Boundary= 1
Downstream Boundary Weight= 0.5
Weight of XSs Associated with DS Boundary= 0.5
Sediment Output Level= 4
Mass or Volume Output= 0
Output Increment Type= 1
Profile and TS Output Increment= 10
XS Output Flag= 0
XS Output Increment= 10
Disregard all LS=0
Disregard all Conn=0
Disregard all Breaches=0
Disregard all Pumps=0

--- C118-00-00.p01 (plan) ---

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Plan Title=Effective Multi-Profile 2015
Short Identifier=Eff+RiskMAP MP
Geom File=g01
Flow File=f01
Encroach Param=-1 ,0,0, 0
FEMA Effective Risk Map Study Multi-Profile May 02, 2019

--- C118-00-00.f02 (steady flow) ---

Flow Title=Effective Floodway 2015
Program Version=4.10
Number of Profiles= 2
Profile Names=1PCT_100yr,Floodway
River Rch & RM=C118-00-00,C118-00-00_0009 ,6143.9
    1986    1986
River Rch & RM=C118-00-00,C118-00-00_0009 ,4109.2
    2420    2420
River Rch & RM=C118-00-00,C118-00-00_0009 ,863.9
    3045    3045
Boundary for River Rch & Prof#=C118-00-00,C118-00-00_0009 , 1
Up Type= 0
Dn Type= 3
Dn Slope=0.0035
Boundary for River Rch & Prof#=C118-00-00,C118-00-00_0009 , 2
Up Type= 0
Dn Type= 1
Dn Known WS=27.87
DSS Import GetInterval= 0
DSS Import GetPeak= 0
DSS Import FillOption= 0

--- C118-00-00.f01 (steady flow) ---

Flow Title=Effective Multi-Profile 2015
Program Version=4.10
Number of Profiles= 6
Profile Names=10PCT_10yr,4PCT_25yr,2PCT_50yr,1PCT_100yr,1PCT_Plus,0.2PCT_500yr
River Rch & RM=C118-00-00,C118-00-00_0009 ,6143.9
    1147    1434    1697    1986    2383    2832
River Rch & RM=C118-00-00,C118-00-00_0009 ,4109.2
    1397    1746    2067    2420    2904    3450
River Rch & RM=C118-00-00,C118-00-00_0009 ,863.9
    1759    2198    2601    3045    3654    4342
Boundary for River Rch & Prof#=C118-00-00,C118-00-00_0009 , 1
Up Type= 0
Dn Type= 3
Dn Slope=0.0035
Boundary for River Rch & Prof#=C118-00-00,C118-00-00_0009 , 2
Up Type= 0
Dn Type= 3
Dn Slope=0.0035
Boundary for River Rch & Prof#=C118-00-00,C118-00-00_0009 , 3
Up Type= 0
Dn Type= 3
Dn Slope=0.0035
Boundary for River Rch & Prof#=C118-00-00,C118-00-00_0009 , 4
Up Type= 0
Dn Type= 3
Dn Slope=0.0035
DSS Import GetInterval= 0
DSS Import GetPeak= 0
DSS Import FillOption= 0

--- C118-00-00.g01 (geometry) ---

Geom Title=C118-00-00 2015
Program Version=4.10

River Reach=C118-00-00      ,C118-00-00_0009
Reach XY= 30
      3135584.33     13808398.65      3135585.27     13808349.11
      3135606.22     13808169.02      3135607.82     13807999.99
        3135651.     13807265.93      3135697.77     13806542.67
      3135692.77     13806437.93        3135726.       13806375.
      3135740.95     13805974.14        3135776.       13805210.
      3135784.75       13805179.      3135816.52     13805157.33
      3135830.91     13805128.54       3135852.5     13805096.16
      3135820.12     13804995.41      3135812.92     13804894.65
      3135830.91     13804833.48      3135802.12     13804761.52
      3135816.52     13804657.17      3135827.31     13804506.04
      3135830.91     13804383.69       3135845.3     13804286.54
      3135874.09     13803973.49       3135863.3     13803901.52
       3135859.7     13803836.75      3135895.68     13803779.18
      3135888.48     13803703.62      3135888.48     13803548.89
      3135895.68     13803358.18      3135899.28     13803034.33

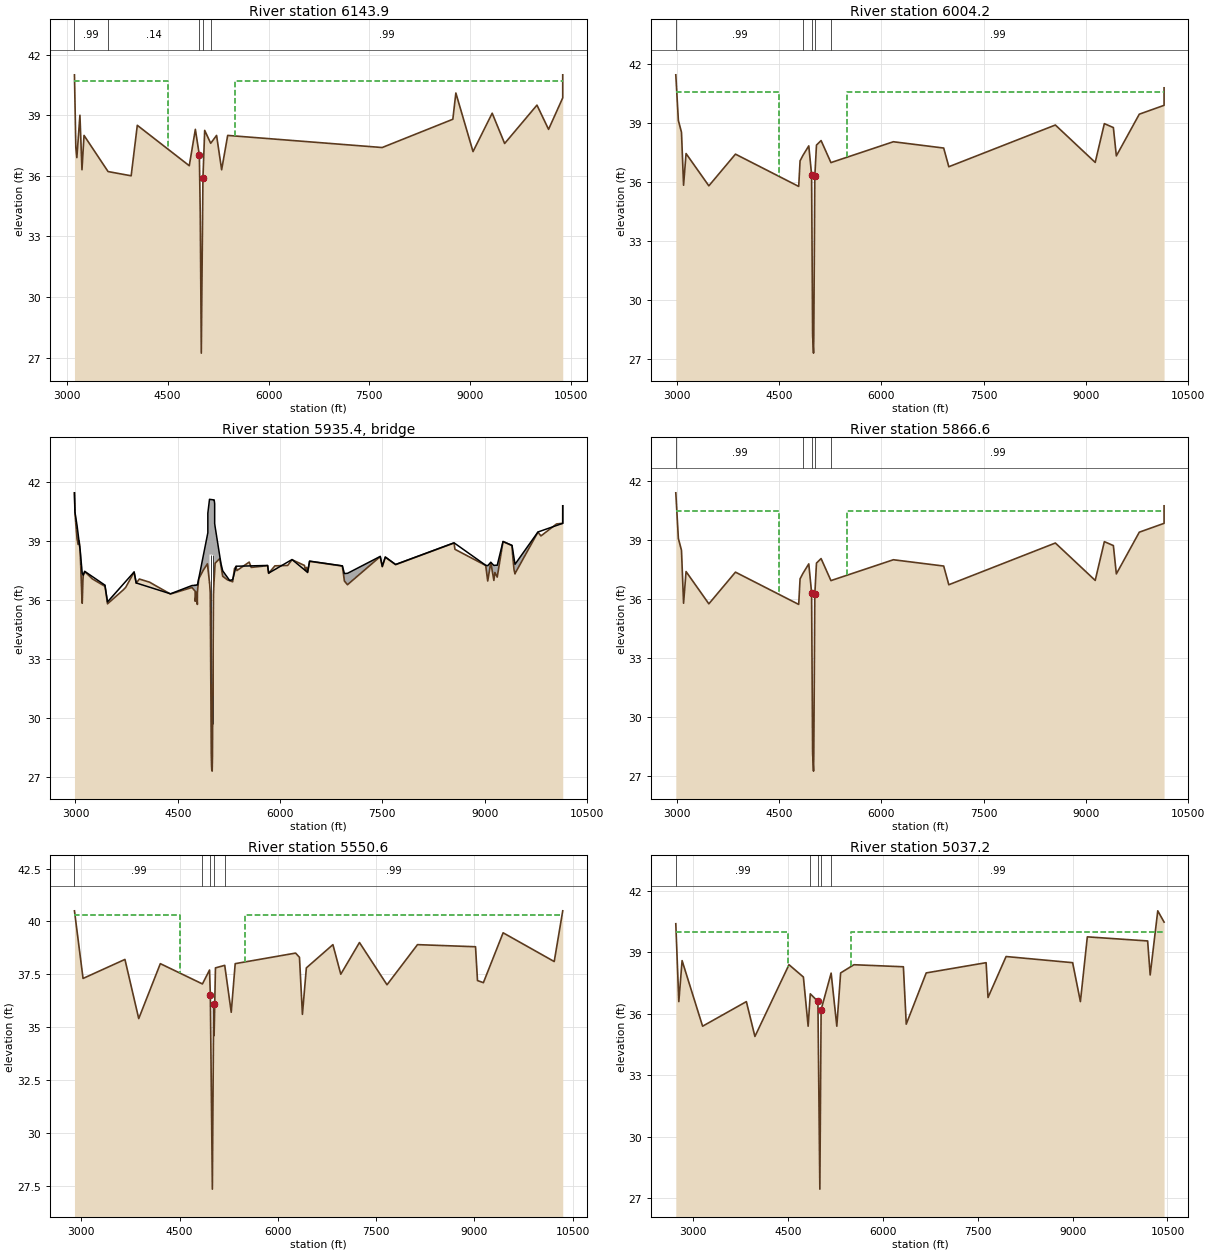
Type RM Length L Ch R = 1 ,6143.9  ,162.4,139.7,101.3
BEGIN DESCRIPTION:
Cross Section 6143.9
END DESCRIPTION:
XS GIS Cut Line= 6
      3137446.19     13808733.19      3136336.04     13808534.79
       3135602.7     13808441.39      3131462.35     13808259.15
      3130612.87     13808235.78      3130212.58     13808218.02
#Sta/Elev= 30
  3113.8      41  3134.3    37.4  3149.5    36.9  3195.2      39  3225.7    36.3
  3256.2      38  3613.8   36.21  3957.1      36  4048.6    38.5  4821.4    36.5
    4912    38.3  4971.4   37.02  4984.6   34.18  5000.3   27.22  5024.7   35.88
  5050.7   38.25    5140   37.61  5227.7      38  5302.8    36.3  5392.9      38
  7690.3    37.4  8741.3    38.8  8786.3    40.1  9041.6    37.2  9326.7    39.1
  9511.9    37.6  9992.6    39.5 10165.1    38.3 10375.8   39.86 10375.9      41
#Mann= 5 , 1 , 0
  3113.8     .99       0  3613.8     .14       0  4971.4     .04       0
  5024.7     .14       0    5140     .99       0
#XS Ineff= 2 , 0
       0    4500   40.68    5500       0   40.68
Permanent Ineff=
       F       F
Bank Sta=4971.4,5024.7
XS Rating Curve= 0 ,0
Exp/Cntr=0.5,0.3

Type RM Length L Ch R = 1 ,6004.2  ,142.7,137.6,135.6
BEGIN DESCRIPTION:
Upstream Section of Bridge/Culvert/Weir
END DESCRIPTION:
XS GIS Cut Line= 6
      3137582.13     13808284.78      3137114.48     13808234.26
      3136132.81     13808386.19      3135593.31     13808301.78
      3135294.59     13808324.34      3130452.56     13808120.45
#Sta/Elev= 30
  2984.7   41.45  3022.5   39.13  3068.2   38.53  3098.7   35.84  3135.1   37.45
  3469.6   35.81  3859.7   37.42  4787.3   35.78  4807.4   37.08    4850   37.36
    4935   37.84  4976.2   36.38  4991.4   28.22  5004.6   27.31  5008.6   28.05
  5023.6    36.3  5047.9   37.88  5115.6   38.11    5260   36.99  6175.5   38.05
  6913.7   37.73  6988.8   36.78  8551.6    38.9  9135.8      37    9270   38.97
  9402.2   38.77  9445.8   37.33  9782.2   39.45 10145.8    39.9 10145.9   40.79
#Mann= 5 , 1 , 0
  2984.7     .99       0    4850     .14       0  4976.2     .04       0
  5023.6     .14       0    5260     .99       0
#XS Ineff= 2 , 0
       0    4500    40.6    5500       0    40.6
Permanent Ineff=
       F       F
Bank Sta=4976.2,5023.6
XS Rating Curve= 0 ,0
Exp/Cntr=0.5,0.3

Type RM Length L Ch R = 3 ,5935.4  ,,,
BEGIN DESCRIPTION:
BELLFORT AVENUE
Structure ID: C18-03
END DESCRIPTION:
Bridge Culvert--1,0,-1,-1, 0
Deck Dist Width WeirC Skew NumUp NumDn MinLoCord MaxHiCord MaxSubmerge Is_Ogee
10,117.6,2.6,0, 60, 60, , , 0.95, 0, 1,1,,
  2984.7  2992.1  3022.5  3068.2  3098.7  3113.9  3135.1  3431.5  3469.6  3859.7
  3890.3  4392.7  4708.2  4755.1  4755.6    4772  4787.3  4787.8  4807.4 4940.79
  4940.9  4965.3 4965.41  4965.5 5033.79  5033.9  5040.9 5041.01  5047.9  5115.6
  5133.4  5158.7    5260  5305.4  5355.1  5817.5  5832.5  6175.5  6403.3  6433.3
  6913.7  6943.8  6988.8  7469.3  7499.3  7543.6  7694.5  8551.6  9015.7  9045.7
  9090.7  9135.8  9150.8  9185.2    9270  9402.2  9445.8  9782.2 10145.8 10145.9
   41.46   40.48   39.81   38.55   37.37   37.28   37.47   36.77   35.92   37.44
   36.88   36.33   36.75   36.76   36.77   36.77   36.78   36.78    37.1   39.43
   40.43   41.13   41.13   41.13    41.1    41.1   40.91   39.91   39.73   38.25
   37.87    37.5   37.01   37.05   37.73   37.77   37.38   38.07   37.42   37.99
   37.75   37.36   37.37   38.23   37.72    38.2   37.82   38.92   37.78   37.76
   37.93   37.77   37.78   37.78   38.99   38.79   37.83   39.47   39.91    40.8
   41.46   40.48   39.14   38.54   35.85   37.27   37.46   36.76   35.82   37.43
   36.87   36.32   36.65   36.46   35.95   36.41   35.79   36.38   37.09   37.67
   37.67   36.91   36.91   38.33    38.3   37.07   37.48   37.49   37.89   38.12
   37.75   37.22      37   36.94   37.72   37.76   37.37   38.06   37.41   37.98
   37.74   36.98   36.79   38.22   37.71   38.19   37.81   38.91   37.77   36.98
   37.92   37.01   37.41   37.18   38.98   38.78   37.34   39.46   39.91    40.8
  2984.7  2992.1  3022.5  3068.2  3098.7  3113.9  3135.1  3431.5  3469.6  3859.7
  3890.3  4392.7  4708.2  4755.1  4755.6    4772  4787.3  4787.8  4807.4 4940.79
  4940.9  4965.3 4965.41  4965.5 5033.79  5033.9  5040.9 5041.01  5047.9  5115.6
  5133.4  5158.7    5260  5305.4  5355.1  5817.5  5832.5  6175.5  6403.3  6433.3
  6913.7  6943.8  6988.8  7469.3  7499.3  7543.6  7694.5  8551.6  9015.7  9045.7
  9090.7  9135.8  9150.8  9185.2    9270  9402.2  9445.8  9782.2 10145.8 10145.9
   41.46   40.48   39.81   38.55   37.37   37.28   37.47   36.77   35.92   37.44
   36.88   36.33   36.75   36.76   36.77   36.77   36.78   36.78    37.1   39.43
   40.43   41.13   41.13   41.13    41.1    41.1   40.91   39.91   39.73   38.25
   37.87    37.5   37.01   37.05   37.73   37.77   37.38   38.07   37.42   37.99
   37.75   37.36   37.37   38.23   37.72    38.2   37.82   38.92   37.78   37.76
   37.93   37.77   37.78   37.78   38.99   38.79   37.83   39.47   39.91    40.8
    41.4   40.42   39.08   38.48   35.79   37.21    37.4    36.7   35.76   37.37
   36.81   36.26   36.59    36.4   35.89   36.35   35.73   36.32   37.03   37.61
   37.61   36.85   36.85   38.27   38.24   37.01   37.42   37.43   37.83   38.06
   37.69   37.16   36.94   36.88   37.66    37.7   37.31      38   37.35   37.92
   37.68   36.92   36.73   38.16   37.65   38.13   37.75   38.85   37.71   36.92
   37.86   36.95   37.35   37.12   38.92   38.72   37.28    39.4   39.85   40.74
Pier Skew, UpSta & Num, DnSta & Num=  ,4988.4, 2 ,4988.4, 2 , 0 , 0 , 0 ,,
     1.2     1.2
   28.51   39.32
     1.2     1.2
   28.45   39.26
Pier Skew, UpSta & Num, DnSta & Num=  ,5011.5, 2 ,5011.5, 2 , 0 , 0 , 0 ,,
     1.2     1.2
   28.38   39.31
     1.2     1.2
   28.32   39.25
Abutment Skew #Up #Dn= , 2 , 2
  4965.3    4967
   38.33   36.86
  4965.3    4967
   38.27    36.8
Abutment Skew #Up #Dn= , 2 , 2
  5032.8 5033.99
   37.01    38.3
  5032.8 5033.99
   36.95   38.24
BR Coef= 1 , 1 , 0 ,1.25, 0 ,,,0.8,0,2,0,
WSPro=,,,, 1 ,,,, 0 ,,,, 0 ,,,,-1 ,-1 ,-1 , 0 , 0 , 0 , 0 , 0
BR U #Sta/Elev= 126
  2984.7   41.46  2992.1   40.48  2993.3   40.42  3005.6   39.81  3007.3   39.79
  3013.3   39.53  3022.5   39.14  3037.8   38.84    3053   39.02  3068.2   38.54
  3096.3   35.89  3098.7   35.85  3109.2   37.01  3113.9   37.27  3116.4   37.29
  3135.1   37.46  3246.2   37.09  3294.6   36.99    3417   36.74  3431.5   36.76
  3457.2   36.13  3469.6   35.82  3701.1   36.53  3736.8   36.66  3838.8    37.3
  3859.7   37.43  3890.3   36.87  3936.5   37.08  4086.4   36.92  4186.7   36.72
  4309.9   36.48  4392.7   36.32  4453.3   36.38  4708.1   36.65  4708.2   36.65
  4755.1   36.46  4755.6   35.95    4772   36.41  4787.3   35.79  4787.8   36.38
  4802.4   36.91  4807.4   37.09    4850   37.37  4874.5   37.53    4882   37.57
    4935   37.85 4940.79   37.67  4940.9   37.67 4941.01   37.66  4941.9   37.64
  4965.3   36.91 4965.41   36.91  4965.5   36.91  4966.9   36.86    4967   36.86
  4976.2   36.39  4988.4   29.83  4991.4   28.23  4995.7   27.58  4998.9   27.39
  5004.6   27.32  5008.6   28.06  5011.5   29.73  5023.6   36.31  5032.7      37
  5032.8   37.01  5033.7   37.06 5033.79   37.06  5033.9   37.07    5034   37.08
 5040.79   37.47  5040.9   37.48 5041.01   37.49  5047.9   37.89    5052    37.9
  5115.6   38.12  5133.4   37.75  5158.7   37.22    5209   37.09  5228.2   37.04
    5260      37  5305.4   36.94  5307.2   37.03  5309.3   37.08  5332.1   37.61
  5355.1   37.72  5367.2   37.51  5547.3   37.94  5577.4   37.67  5817.5   37.76
  5832.5   37.37  5924.3   37.75    6112   37.77  6175.5   38.06  6358.2   37.77
  6373.3   37.51  6388.3   37.67  6403.3   37.41  6433.3   37.98  6913.7   37.74
  6943.8   36.98  6988.8   36.79  7469.3   38.22  7499.3   37.71  7543.6   38.19
  7694.5   37.81  8551.6   38.91  8565.2   38.59  9015.7   37.77  9045.7   36.98
  9090.7   37.92  9135.8   37.01  9150.8   37.41  9185.2   37.18    9270   38.98
  9402.2   38.78  9409.9   38.36  9431.3   37.56  9445.8   37.34    9451   37.39
  9782.2   39.46    9822   39.29  9826.2   39.27 10055.8   39.88 10145.8   39.91
 10145.9    40.8
BR U #Mann= 5
  2984.7     .99    4850     .14  4976.2     .04  5023.6     .14    5260     .99
BR U Banks=4976.2,5023.6
BR D #Sta/Elev= 126
  2984.7    41.4  2992.1   40.42  2993.3   40.36  3005.6   39.75  3007.3   39.73
  3013.3   39.47  3022.5   39.08  3037.8   38.78    3053   38.96  3068.2   38.48
  3096.3   35.83  3098.7   35.79  3109.2   36.95  3113.9   37.21  3116.4   37.23
  3135.1    37.4  3246.2   37.03  3294.6   36.93    3417   36.68  3431.5    36.7
  3457.2   36.07  3469.6   35.76  3701.1   36.47  3736.8    36.6  3838.8   37.24
  3859.7   37.37  3890.3   36.81  3936.5   37.02  4086.4   36.86  4186.7   36.66
  4309.9   36.42  4392.7   36.26  4453.3   36.32  4708.1   36.59  4708.2   36.59
  4755.1    36.4  4755.6   35.89    4772   36.35  4787.3   35.73  4787.8   36.32
  4802.4   36.85  4807.4   37.03    4850   37.31  4874.5   37.47    4882   37.51
    4935   37.79 4940.79   37.61  4940.9   37.61 4941.01    37.6  4941.9   37.58
  4965.3   36.85 4965.41   36.85  4965.5   36.85  4966.9    36.8    4967    36.8
  4976.2   36.33  4988.4   29.77  4991.4   28.17  4995.7   27.52  4998.9   27.33
  5004.6   27.26  5008.6      28  5011.5   29.67  5023.6   36.25  5032.7   36.94
  5032.8   36.95  5033.7      37 5033.79      37  5033.9   37.01    5034   37.02
 5040.79   37.41  5040.9   37.42 5041.01   37.43  5047.9   37.83    5052   37.84
  5115.6   38.06  5133.4   37.69  5158.7   37.16    5209   37.03  5228.2   36.98
    5260   36.94  5305.4   36.88  5307.2   36.97  5309.3   37.02  5332.1   37.55
  5355.1   37.66  5367.2   37.45  5547.3   37.88  5577.4   37.61  5817.5    37.7
  5832.5   37.31  5924.3   37.69    6112   37.71  6175.5      38  6358.2   37.71
  6373.3   37.45  6388.3   37.61  6403.3   37.35  6433.3   37.92  6913.7   37.68
  6943.8   36.92  6988.8   36.73  7469.3   38.16  7499.3   37.65  7543.6   38.13
  7694.5   37.75  8551.6   38.85  8565.2   38.53  9015.7   37.71  9045.7   36.92
  9090.7   37.86  9135.8   36.95  9150.8   37.35  9185.2   37.12    9270   38.92
  9402.2   38.72  9409.9    38.3  9431.3    37.5  9445.8   37.28    9451   37.33
  9782.2    39.4    9822   39.23  9826.2   39.21 10055.8   39.82 10145.8   39.85
 10145.9   40.74
BR D #Mann= 5
  2984.7     .99    4850     .14  4976.2     .04  5023.6     .14    5260     .99
BR D Banks=4976.2,5023.6
BC Design=,, 0 ,, 0 ,,,,,,
BC HTab HWMax=41.45
BC Use User HTab Curves=0
BC User HTab FreeFlow(D)= 0

Type RM Length L Ch R = 1 ,5866.6  ,317.6,316,315.8
BEGIN DESCRIPTION:
Downstream Section of Bridge/Culvert/Weir
END DESCRIPTION:
XS GIS Cut Line= 6
      3137595.45     13808147.83       3137127.8      13808097.3
      3136146.13     13808249.23      3135606.63     13808164.82
      3135307.91     13808187.38      3130465.88     13807983.49
#Sta/Elev= 30
  2984.7    41.4  3022.5   39.08  3068.2   38.48  3098.7   35.79  3135.1    37.4
  3469.6   35.76  3859.7   37.37  4787.3   35.73  4807.4   37.03    4850   37.31
    4935   37.79  4976.2   36.33  4991.4   28.17  5004.6   27.26  5008.6      28
  5023.6   36.25  5047.9   37.83  5115.6   38.06    5260   36.94  6175.5      38
  6913.7   37.68  6988.8   36.73  8551.6   38.85  9135.8   36.95    9270   38.92
  9402.2   38.72  9445.8   37.28  9782.2    39.4 10145.8   39.85 10145.9   40.74
#Mann= 5 , 1 , 0
  2984.7     .99       0    4850     .14       0  4976.2     .04       0
  5023.6     .14       0    5260     .99       0
#XS Ineff= 2 , 0
       0    4500    40.5    5500       0    40.5
Permanent Ineff=
       F       F
Bank Sta=4976.2,5023.6
XS Rating Curve= 0 ,0
Exp/Cntr=0.5,0.3

Type RM Length L Ch R = 1 ,5550.6  ,531.2,513.4,505.2
BEGIN DESCRIPTION:
Cross Section 5550.6-Interpolated
END DESCRIPTION:
XS GIS Cut Line= 6
      3137602.16     13808115.23      3137480.48     13807911.86
      3136451.72     13807838.38      3135451.74      13807842.5
      3134487.61     13807723.47      3130278.83     13807528.85
#Sta/Elev= 30
  2896.3    40.5  3027.6    37.3    3667    38.2  3877.5    35.4  4207.3      38
    4850   37.04  4958.5    37.7  4970.5    36.5  5001.4   27.33  5021.5   36.09
  5028.2    34.6  5048.6    37.8    5190   37.92  5289.6    35.7  5350.1      38
  6271.9    38.5  6331.2    38.3  6376.2    35.6  6436.3    37.8  6841.6    38.9
  6961.7    37.5    7247      39  7667.4      37  8132.8    38.9  9018.6    38.8
  9048.6    37.2  9138.7    37.1  9439.8   39.46 10219.8    38.1 10349.9    40.5
#Mann= 5 , 1 , 0
  2896.3     .99       0    4850     .14       0  4970.5     .04       0
  5021.5     .14       0    5190     .99       0
#XS Ineff= 2 , 0
       0    4500    40.3    5500       0    40.3
Permanent Ineff=
       F       F
Bank Sta=4970.5,5021.5
XS Rating Curve= 0 ,0
Exp/Cntr=0.3,0.1

Type RM Length L Ch R = 1 ,5037.2  ,643.9,694.2,693.3
BEGIN DESCRIPTION:
Cross Section 5037.2
END DESCRIPTION:
XS GIS Cut Line= 6
      3137918.22     13807191.27      3136206.58     13807330.82
      3135566.74     13807334.82       3135139.3     13807278.89
      3131405.23     13807006.88      3130216.24     13806949.27
#Sta/Elev= 30
  2722.7    40.4  2770.5    36.6  2822.4    38.6  3146.7    35.4    3839    36.6
  3974.4    34.9  4513.5    38.4    4741    37.8  4816.1    35.4    4850   36.98
  4970.6   36.61  5001.4   27.45  5021.5   36.21    5180   37.99  5269.7    35.4
    5330      38  5540.8    38.4  6322.9    38.3    6368    35.5  6683.8      38
  7631.3    38.5  7661.4    36.8  7947.2    38.8  8999.9    38.5  9122.7    36.6
  9232.4   39.76 10186.4   39.56 10226.4    37.9 10346.4   41.03 10446.4   40.48
#Mann= 5 , 1 , 0
  2722.7     .99       0    4850     .14       0  4970.6    .045       0
  5021.5     .14       0    5180     .99       0
#XS Ineff= 2 , 0
       0    4500      40    5500       0      40
Permanent Ineff=
       F       F
Bank Sta=4970.6,5021.5
XS Rating Curve= 0 ,0
Exp/Cntr=0.3,0.1

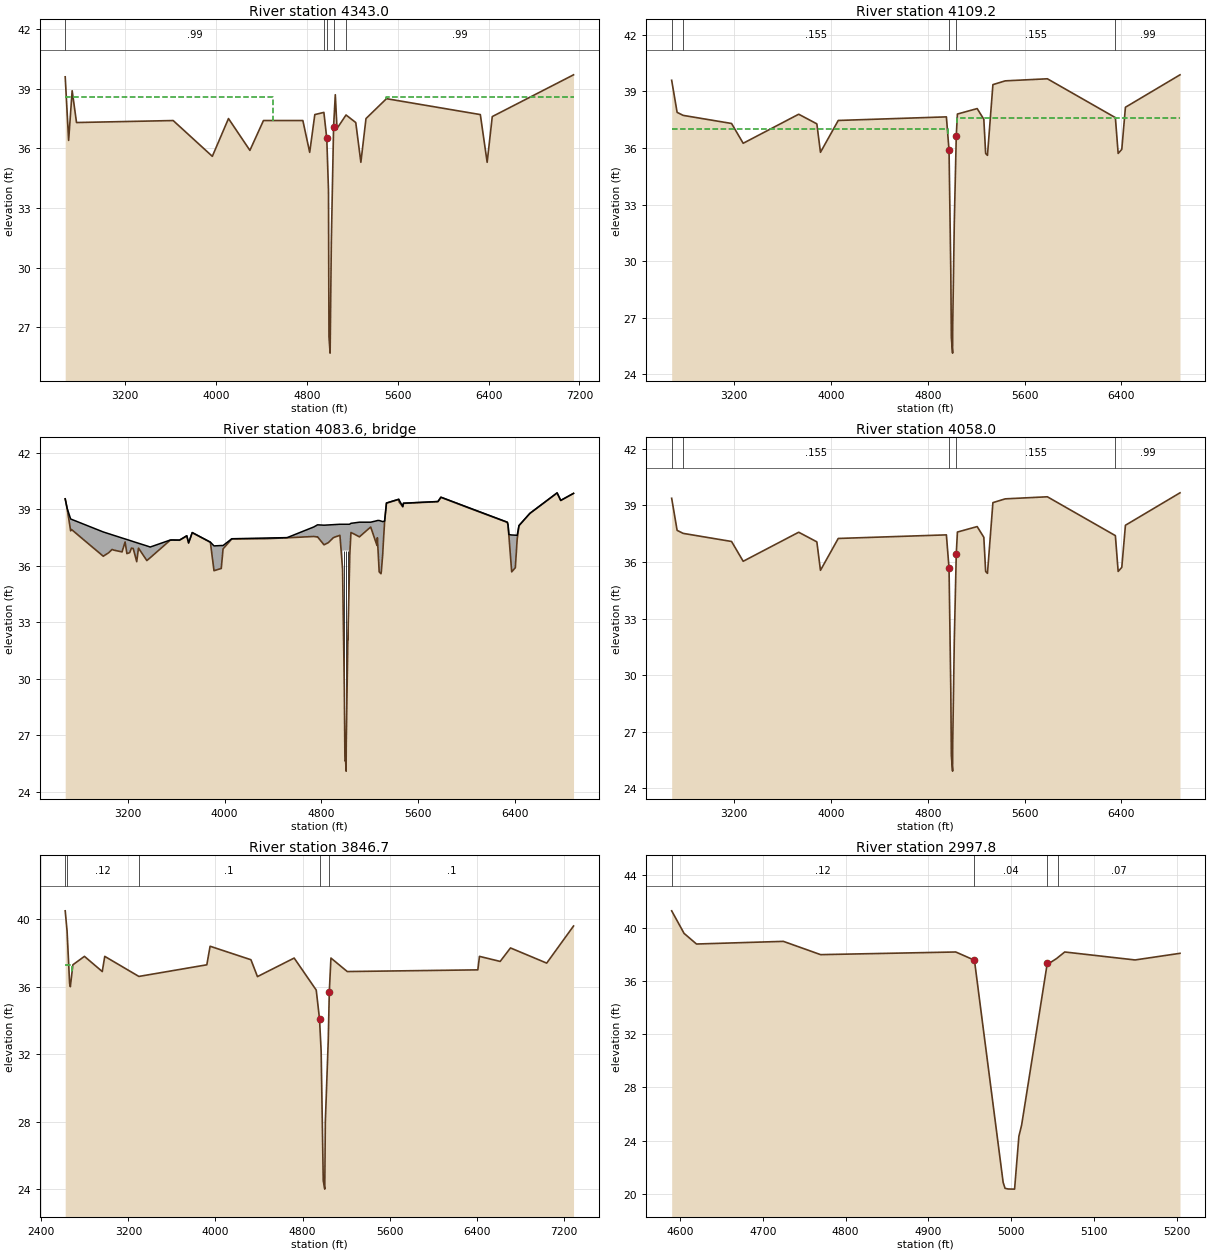
Type RM Length L Ch R = 1 ,4343.0  ,233.7,233.8,364.2
BEGIN DESCRIPTION:
Cross Section 4343.0-Interpolated
END DESCRIPTION:
XS GIS Cut Line= 5
      3138011.54      13806821.1      3136968.14     13806735.45
      3135685.85     13806643.31      3135516.93     13806643.31
      3133546.28     13806534.05
#Sta/Elev= 30
  2672.7    39.6  2702.9    36.4  2733.9    38.9  2772.4    37.3  3623.2    37.4
  3967.9    35.6  4110.2    37.5  4298.7    35.9  4418.1    37.4  4764.9    37.4
  4825.1    35.8  4870.2    37.7    4950   37.81  4975.5    36.5  4990.5    33.9
  4994.8   26.52  5004.9    25.7  5015.6    31.3  5035.5    37.1  5050.5    38.7
  5065.5      37    5145   37.68  5230.6    37.3  5275.7    35.3  5320.7    37.5
    5501    38.5  6327.3    37.7  6387.4    35.3  6432.4    37.6  7147.8    39.7
#Mann= 5 , 1 , 0
  2672.7     .99       0    4950    .155       0  4975.5     .05       0
  5035.5    .155       0    5145     .99       0
#XS Ineff= 2 , 0
       0    4500    38.6    5500       0    38.6
Permanent Ineff=
       F       F
Bank Sta=4975.5,5035.5
XS Rating Curve= 0 ,0
Exp/Cntr=0.5,0.3

Type RM Length L Ch R = 1 ,4109.2  ,51.5,51.2,51
BEGIN DESCRIPTION:
Upstream Section of Bridge/Culvert/Weir
END DESCRIPTION:
XS GIS Cut Line= 6
        3138036.     13806513.34       3136442.1     13806442.54
      3135894.75     13806417.92      3135389.54     13806395.42
      3134955.46     13806384.86      3133835.68     13806341.79
#Sta/Elev= 30
  2681.7   39.59  2726.7   37.89  2776.2   37.73  3176.9    37.3  3273.2   36.25
  3732.2   37.79  3882.3   37.28  3912.3   35.77  4059.3   37.46  4953.7   37.65
  4975.6   35.87  4990.2   29.39  4994.7   25.94  5004.9   25.12  5005.9   26.57
  5019.1   32.07  5035.4   36.64  5044.8    37.8  5208.2   38.09  5263.3   37.52
  5278.3   35.71  5293.3   35.61  5338.4   39.36  5439.9   39.56  5788.8   39.67
  6351.2   37.61  6374.2   35.71  6404.3   35.93  6434.3   38.16  6885.6   39.88
#Mann= 5 , 1 , 0
  2681.7     .99       0  2776.2    .155       0  4975.6     .05       0
  5035.4    .155       0  6351.2     .99       0
#XS Ineff= 2 , 0
       0    4965      37    5041       0    37.6
Permanent Ineff=
       F       F
Bank Sta=4975.6,5035.4
XS Rating Curve= 0 ,0
Exp/Cntr=0.5,0.3

Type RM Length L Ch R = 3 ,4083.6  ,,,
BEGIN DESCRIPTION:
VASSER STREET
Structure ID: C18-01
END DESCRIPTION:
Bridge Culvert--1,0,-1,-1, 0
Deck Dist Width WeirC Skew NumUp NumDn MinLoCord MaxHiCord MaxSubmerge Is_Ogee
10,31.2,2.6,0, 60, 60, , , 0.95, 0, 1,1,,
  2681.7  2696.7  2726.7  2734.6  2996.8  3069.4  3151.9  3176.9  3191.9  3244.1
  3273.2  3287.8    3357  3384.6  3549.8  3627.1  3687.2  3702.2  3732.2  3882.3
  3912.3  3972.3  3987.3  4059.3  4517.2  4738.7  4768.4  4823.1  4953.7 4975.21
  4975.3 5031.09  5031.2  5035.4  5044.8  5115.3  5208.2  5260.2  5263.3  5278.3
  5293.3  5308.3  5323.4  5338.4  5439.9  5473.5  5478.9  5764.5  5788.8  6338.3
  6344.2  6351.2  6374.2  6404.3  6419.3  6434.3  6524.3  6749.7  6779.7  6885.6
   39.56   39.08   38.49   38.47    37.8   37.65   37.48   37.43    37.4   37.29
   37.23    37.2   37.06      37   37.37   37.37    37.6   37.22   37.77   37.26
   37.06   37.08   37.08   37.44    37.5   38.07   38.18   38.16   38.21   38.21
   38.21   38.21   38.21   38.22   38.26   38.32   38.32    38.4   38.41   38.41
   38.38   38.35   38.38   39.34   39.54   39.15   39.33   39.42   39.65   38.32
   38.17   37.66   37.64   37.63   37.62   38.14   38.79   39.88   39.48   39.85
   39.56   39.08   37.86   37.93   36.51   36.87   36.74   37.27   36.65   36.92
   36.22   36.94   36.28   36.43   37.36   37.36   37.59   37.21   37.76   37.25
   35.74   35.86    36.9   37.43   37.49   37.56   37.54   37.12   37.62   35.87
   36.81   36.81   35.43   36.61   37.77   37.54   38.06   37.08   37.49   35.68
   35.58   36.67   38.37   39.33   39.53   39.14   39.32   39.41   39.64   38.31
   38.16   37.58   35.68    35.9   37.39   38.13   38.78   39.87   39.47   39.85
  2681.7  2696.7  2726.7  2734.6  2996.8  3069.4  3151.9  3176.9  3191.9  3244.1
  3273.2  3287.8    3357  3384.6  3549.8  3627.1  3687.2  3702.2  3732.2  3882.3
  3912.3  3972.3  3987.3  4059.3  4517.2  4738.7  4768.4  4823.1  4953.7 4975.21
  4975.3 5031.09  5031.2  5035.4  5044.8  5115.3  5208.2  5260.2  5263.3  5278.3
  5293.3  5308.3  5323.4  5338.4  5439.9  5473.5  5478.9  5764.5  5788.8  6338.3
  6344.2  6351.2  6374.2  6404.3  6419.3  6434.3  6524.3  6749.7  6779.7  6885.6
   39.56   39.08   38.49   38.47    37.8   37.65   37.48   37.43    37.4   37.29
   37.23    37.2   37.06      37   37.37   37.37    37.6   37.22   37.77   37.26
   37.06   37.08   37.08   37.44    37.5   38.07   38.18   38.16   38.21   38.21
   38.21   38.21   38.21   38.22   38.26   38.32   38.32    38.4   38.41   38.41
   38.38   38.35   38.38   39.34   39.54   39.15   39.33   39.42   39.65   38.32
   38.17   37.66   37.64   37.63   37.62   38.14   38.79   39.88   39.48   39.85
   39.42   38.94   37.72   37.79   36.37   36.73    36.6   37.13   36.51   36.78
   36.08    36.8   36.14   36.29   37.22   37.22   37.45   37.07   37.62   37.11
    35.6   35.72   36.76   37.29   37.35   37.42    37.4   36.98   37.48   35.73
   36.67   36.67   35.29   36.47   37.63    37.4   37.92   36.94   37.35   35.54
   35.44   36.53   38.23   39.19   39.39      39   39.18   39.27    39.5   38.17
   38.02   37.44   35.54   35.76   37.25   37.99   38.64   39.73   39.33   39.71
Pier Skew, UpSta & Num, DnSta & Num=  ,4990.2, 2 ,4990.2, 2 , 0 , 0 , 0 ,,
       1       1
   27.98   37.81
       1       1
   27.84   37.67
Pier Skew, UpSta & Num, DnSta & Num=  ,5004.9, 2 ,5004.9, 2 , 0 , 0 , 0 ,,
       1       1
   24.16   37.81
       1       1
   24.02   37.67
Pier Skew, UpSta & Num, DnSta & Num=  ,5019.1, 2 ,5019.1, 2 , 0 , 0 , 0 ,,
       1       1
   30.83   37.81
       1       1
   30.69   37.67
Abutment Skew #Up #Dn= , 2 , 2
  4975.1  4994.8
   36.81   25.89
  4975.1  4994.8
   36.67   25.75
Abutment Skew #Up #Dn= , 2 , 2
  5005.9 5031.29
   26.54   36.81
  5005.9 5031.29
    26.4   36.67
BR Coef= 1 , 1 , 0 ,1.25, 0 ,,,0.8,-1,2,0,
WSPro=,,,, 1 ,,,, 0 ,,,, 0 ,,,,-1 ,-1 ,-1 , 0 , 0 , 0 , 0 , 0
BR U #Sta/Elev= 108
  2681.7   39.56  2696.7   39.08  2724.6   37.95  2726.7   37.86  2734.6   37.93
  2776.2    37.7  2994.6   36.52  2996.8   36.51  3041.9    36.7  3069.4   36.87
  3086.9   36.83  3151.9   36.74  3176.9   37.27  3191.9   36.65    3215    36.7
  3229.5   36.94  3244.1   36.92  3273.2   36.22  3287.8   36.94    3357   36.28
  3384.6   36.43  3549.8   37.36  3564.3   37.38  3627.1   37.36  3664.6    37.5
  3687.2   37.59  3702.2   37.21  3732.2   37.76  3882.3   37.25  3912.3   35.74
  3972.3   35.86  3987.3    36.9  4059.3   37.43  4064.6   37.43  4335.9   37.44
  4517.2   37.49  4738.7   37.56  4768.3   37.53  4768.4   37.54  4769.8   37.53
  4821.5   37.12  4823.1   37.12  4857.4   37.23  4900.3    37.5  4903.8   37.51
  4953.7   37.62 4974.69   35.91  4974.8   35.91 4974.91    35.9    4975   35.89
  4975.1   35.88 4975.21   35.87  4975.3   35.86  4975.6   35.84  4990.2   29.36
  4994.7   25.91  4994.8   25.89  4996.3   25.63  5000.6   25.67  5004.9   25.09
  5005.2   25.63  5005.8   26.41  5005.9   26.54  5019.1   32.04 5031.09    35.4
  5031.2   35.43  5031.3   35.46 5031.39   35.49  5031.5   35.52 5031.61   35.55
  5035.4   36.61  5044.8   37.77  5070.7   37.69  5115.3   37.54  5148.8   37.73
  5176.9   37.89  5208.2   38.06  5260.2   37.08  5263.3   37.49  5271.7   36.48
  5278.3   35.68  5293.3   35.58  5296.3   35.71  5308.3   36.67  5310.6   36.99
  5323.4   38.37  5330.8   38.84  5338.4   39.33  5439.9   39.53  5443.5   39.39
  5473.5   39.14  5478.9   39.32  5764.5   39.41  5788.8   39.64  6033.8   39.04
  6338.3   38.31  6344.2   38.16  6351.2   37.58  6374.2   35.68  6404.3    35.9
  6419.3   37.39  6434.3   38.13    6445   38.21  6524.3   38.78  6749.7   39.87
  6779.7   39.47  6862.6   39.77  6885.6   39.85
BR U #Mann= 5
  2681.7     .99  2776.2    .155  4975.6     .05  5035.4    .155  6351.2     .99
BR U Banks=4975.6,5035.4
BR D #Sta/Elev= 108
  2681.7   39.42  2696.7   38.94  2724.6   37.81  2726.7   37.72  2734.6   37.79
  2776.2   37.56  2994.6   36.38  2996.8   36.37  3041.9   36.56  3069.4   36.73
  3086.9   36.69  3151.9    36.6  3176.9   37.13  3191.9   36.51    3215   36.56
  3229.5    36.8  3244.1   36.78  3273.2   36.08  3287.8    36.8    3357   36.14
  3384.6   36.29  3549.8   37.22  3564.3   37.24  3627.1   37.22  3664.6   37.36
  3687.2   37.45  3702.2   37.07  3732.2   37.62  3882.3   37.11  3912.3    35.6
  3972.3   35.72  3987.3   36.76  4059.3   37.29  4064.6   37.29  4335.9    37.3
  4517.2   37.35  4738.7   37.42  4768.3   37.39  4768.4    37.4  4769.8   37.39
  4821.5   36.98  4823.1   36.98  4857.4   37.09  4900.3   37.36  4903.8   37.37
  4953.7   37.48 4974.69   35.77  4974.8   35.77 4974.91   35.76    4975   35.75
  4975.1   35.74 4975.21   35.73  4975.3   35.72  4975.6    35.7  4990.2   29.22
  4994.7   25.77  4994.8   25.75  4996.3   25.49  5000.6   25.53  5004.9   24.95
  5005.2   25.49  5005.8   26.27  5005.9    26.4  5019.1    31.9 5031.09   35.26
  5031.2   35.29  5031.3   35.32 5031.39   35.35  5031.5   35.38 5031.61   35.41
  5035.4   36.47  5044.8   37.63  5070.7   37.55  5115.3    37.4  5148.8   37.59
  5176.9   37.75  5208.2   37.92  5260.2   36.94  5263.3   37.35  5271.7   36.34
  5278.3   35.54  5293.3   35.44  5296.3   35.57  5308.3   36.53  5310.6   36.85
  5323.4   38.23  5330.8    38.7  5338.4   39.19  5439.9   39.39  5443.5   39.25
  5473.5      39  5478.9   39.18  5764.5   39.27  5788.8    39.5  6033.8    38.9
  6338.3   38.17  6344.2   38.02  6351.2   37.44  6374.2   35.54  6404.3   35.76
  6419.3   37.25  6434.3   37.99    6445   38.07  6524.3   38.64  6749.7   39.73
  6779.7   39.33  6862.6   39.63  6885.6   39.71
BR D #Mann= 5
  2681.7     .99  2776.2    .155  4975.6     .05  5035.4    .155  6351.2     .99
BR D Banks=4975.6,5035.4
BC Design=,, 0 ,, 0 ,,,,,,
BC HTab HWMax=39.9
BC Use User HTab Curves=0
BC User HTab FreeFlow(D)= 0

Type RM Length L Ch R = 1 ,4058.0  ,213.2,211.3,210
BEGIN DESCRIPTION:
Downstream Section of Bridge/Culvert/Weir
END DESCRIPTION:
XS GIS Cut Line= 6
      3138037.91     13806462.17        3136444.     13806391.38
      3135896.65     13806366.76      3135391.44     13806344.26
      3134957.36      13806333.7      3133837.59     13806290.63
#Sta/Elev= 30
  2681.7   39.38  2726.7   37.68  2776.2   37.52  3176.9   37.09  3273.2   36.04
  3732.2   37.58  3882.3   37.07  3912.3   35.56  4059.3   37.25  4953.7   37.44
  4975.6   35.66  4990.2   29.18  4994.7   25.73  5004.9   24.91  5005.9   26.36
  5019.1   31.86  5035.4   36.43  5044.8   37.59  5208.2   37.88  5263.3   37.31
  5278.3    35.5  5293.3    35.4  5338.4   39.15  5439.9   39.35  5788.8   39.46
  6351.2    37.4  6374.2    35.5  6404.3   35.72  6434.3   37.95  6885.6   39.67
#Mann= 5 , 1 , 0
  2681.7     .99       0  2776.2    .155       0  4975.6     .05       0
  5035.4    .155       0  6351.2     .99       0
#XS Ineff= 2 , 0
       0    4965    36.4    5041       0    36.4
Permanent Ineff=
       F       F
Bank Sta=4975.6,5035.4
XS Rating Curve= 0 ,0
Exp/Cntr=0.5,0.3

Type RM Length L Ch R = 1 ,3846.7  ,858.9,848.9,848.7
BEGIN DESCRIPTION:
Cross Section 3846.7-Interpolated
END DESCRIPTION:
XS GIS Cut Line= 6
      3138113.71     13806243.16      3135993.95     13806152.65
      3135734.12     13806150.38      3135268.13     13806134.93
      3133850.88     13806121.12      3133452.96     13806206.51
#Sta/Elev= 30
  2618.7    40.5    2636   39.29  2659.1    36.2    2666      36  2689.2    37.3
  2795.4    37.8  2959.4    36.9  2982.3    37.8  3295.9   36.61  3920.4    37.3
  3950.4    38.4  4325.8    37.6  4385.8    36.6  4723.1    37.7    4926    35.8
    4956    34.1    4971    32.2  4990.5    24.5  5004.3      24  5009.5   27.98
  5036.3    32.8  5046.1    35.7  5061.1    37.7  5211.2    36.9  6411.3      37
  6426.3    37.8  6616.5    37.5  6711.4    38.3  7044.2    37.4  7290.8    39.6
#Mann= 5 , 1 , 0
  2618.7      .2       0    2636     .12       0  3295.9      .1       0
    4956     .04       0  5046.1      .1       0
#XS Ineff= 2 , 0
       0  2680.5    37.3               0
Permanent Ineff=
       F       F
Bank Sta=4956,5046.1
XS Rating Curve= 0 ,0
Exp/Cntr=0.3,0.1

Type RM Length L Ch R = 1 ,2997.8  ,888.8,917.1,920.3
BEGIN DESCRIPTION:
Cross Section 2997.8
END DESCRIPTION:
XS GIS Cut Line= 3
      3136184.97     13805235.03      3135752.28     13805237.77
      3135570.81     13805230.92
#Sta/Elev= 22
  4589.9    41.3  4604.9    39.6  4619.9    38.8  4724.9      39  4769.9      38
  4933.2    38.2  4955.8   37.58  4963.2      34  4990.5   20.84  4992.8    20.4
  4996.5   20.35  5004.3   20.34  5009.5   24.32  5012.8   25.16  5035.3      34
  5043.8   37.35  5046.9   37.38  5054.9    37.7  5057.3   37.82  5064.9    38.2
  5149.9    37.6  5204.2    38.1
#Mann= 4 , 1 , 0
  4589.9     .12       0  4955.8     .04       0  5043.8     .12       0
  5057.3     .07       0
Bank Sta=4955.8,5043.8
XS Rating Curve= 0 ,0
Exp/Cntr=0.3,0.1

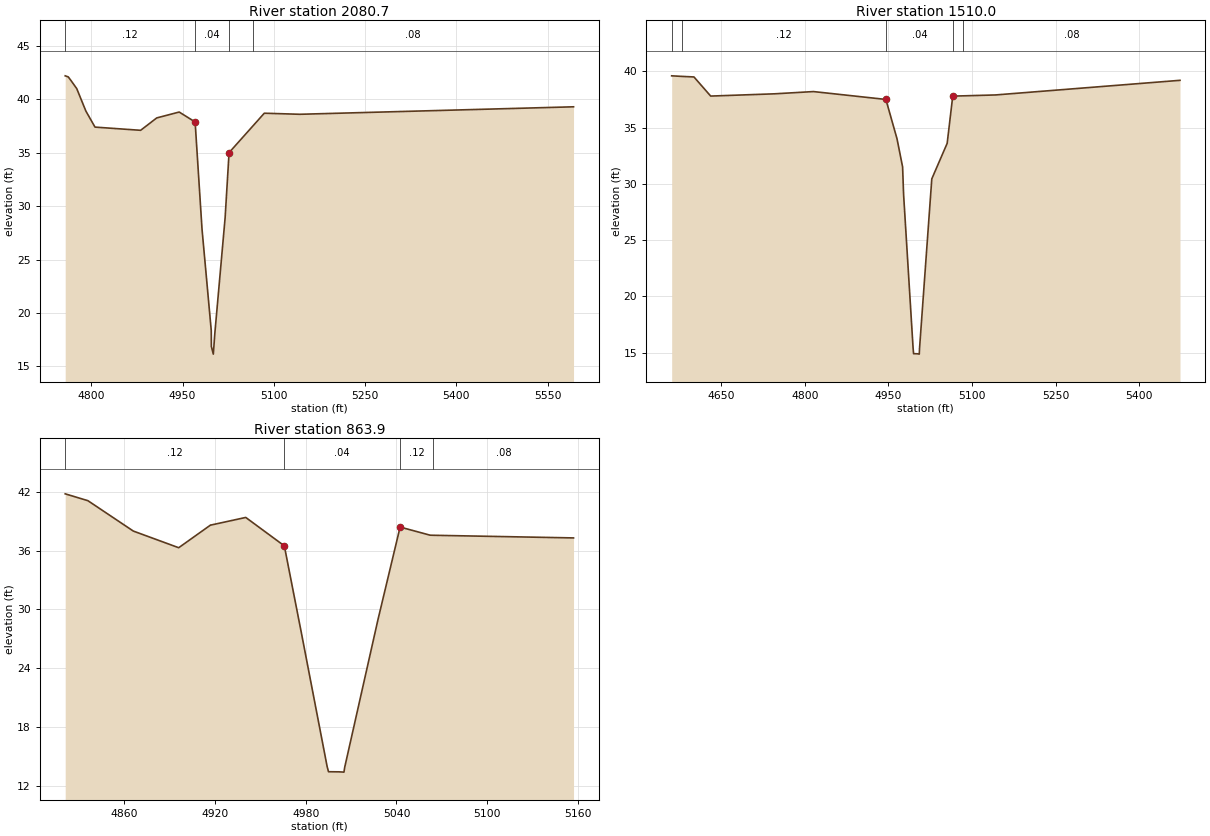
Type RM Length L Ch R = 1 ,2080.7  ,573.8,570.7,566.9
BEGIN DESCRIPTION:
Cross Section 2080.7
END DESCRIPTION:
XS GIS Cut Line= 4
      3136072.82      13804422.1      3136040.39     13804419.15
      3135663.81     13804409.74      3135322.35     13804154.29
#Sta/Elev= 21
    4757    42.2    4762    42.1    4766    41.8    4776      41    4791    38.9
    4806    37.4    4881    37.1  4907.5   38.26  4944.4   38.81  4970.6   37.88
  4981.9   27.87  4997.1   18.36  4997.3   16.86  5000.5   16.15    5003    18.1
  5019.9   28.91  5026.4   35.01    5065   37.47  5084.3    38.7  5142.7    38.6
  5592.7    39.3
#Mann= 4 , 1 , 0
    4757     .12       0  4970.6     .04       0  5026.4     .12       0
    5065     .08       0
Bank Sta=4970.6,5026.4
XS Rating Curve= 0 ,0
Exp/Cntr=0.3,0.1

Type RM Length L Ch R = 1 ,1510.0  ,642.6,646.1,649.5
BEGIN DESCRIPTION:
Cross Section 1510.0-Interpolated
END DESCRIPTION:
XS GIS Cut Line= 4
      3136239.81     13803697.21      3136096.54     13803840.49
      3135699.78     13803845.92      3135412.11      13803969.2
#Sta/Elev= 21
  4560.9    39.6  4579.1   39.55  4600.9    39.5  4630.9    37.8  4745.4      38
  4815.4    38.2  4945.4    37.5  4965.4      34  4975.4    31.5  4977.2   29.04
  4994.2   15.42  4995.1    14.9    5002   14.89  5005.3   14.86  5005.8   15.36
  5027.8   30.44  5055.4    33.6  5065.4    37.8    5084   37.82  5142.2    37.9
  5473.3    39.2
#Mann= 5 , 1 , 0
  4560.9      .2       0  4579.1     .12       0  4945.4     .04       0
  5065.4     .12       0    5084     .08       0
Bank Sta=4945.4,5065.4
XS Rating Curve= 0 ,0
Exp/Cntr=0.3,0.1

Type RM Length L Ch R = 1 ,863.9   ,0,0,0
BEGIN DESCRIPTION:
Cross Section 863.9
END DESCRIPTION:
XS GIS Cut Line= 2
      3136076.28     13803204.63      3135740.49     13803196.02
#Sta/Elev= 19
  4821.1    41.8  4836.1    41.1  4866.1      38  4896.1    36.3  4917.2   38.62
  4917.3   38.61  4940.4   39.39  4965.9   36.49  4977.2   27.58  4994.2   13.96
  4995.1   13.44    5002   13.43  5005.3    13.4  5005.8    13.9  5027.8   28.98
  5042.4   38.41  5062.2   37.58  5064.3   37.57    5157    37.3
#Mann= 4 , 1 , 0
  4821.1     .12       0  4965.9     .04       0  5042.4     .12       0
  5064.3     .08       0
Bank Sta=4965.9,5042.4
XS Rating Curve= 0 ,0
Exp/Cntr=0.3,0.1

Chan Stop Cuts=-1
Use User Specified Reach Order=0
Composite Channel Slope=5